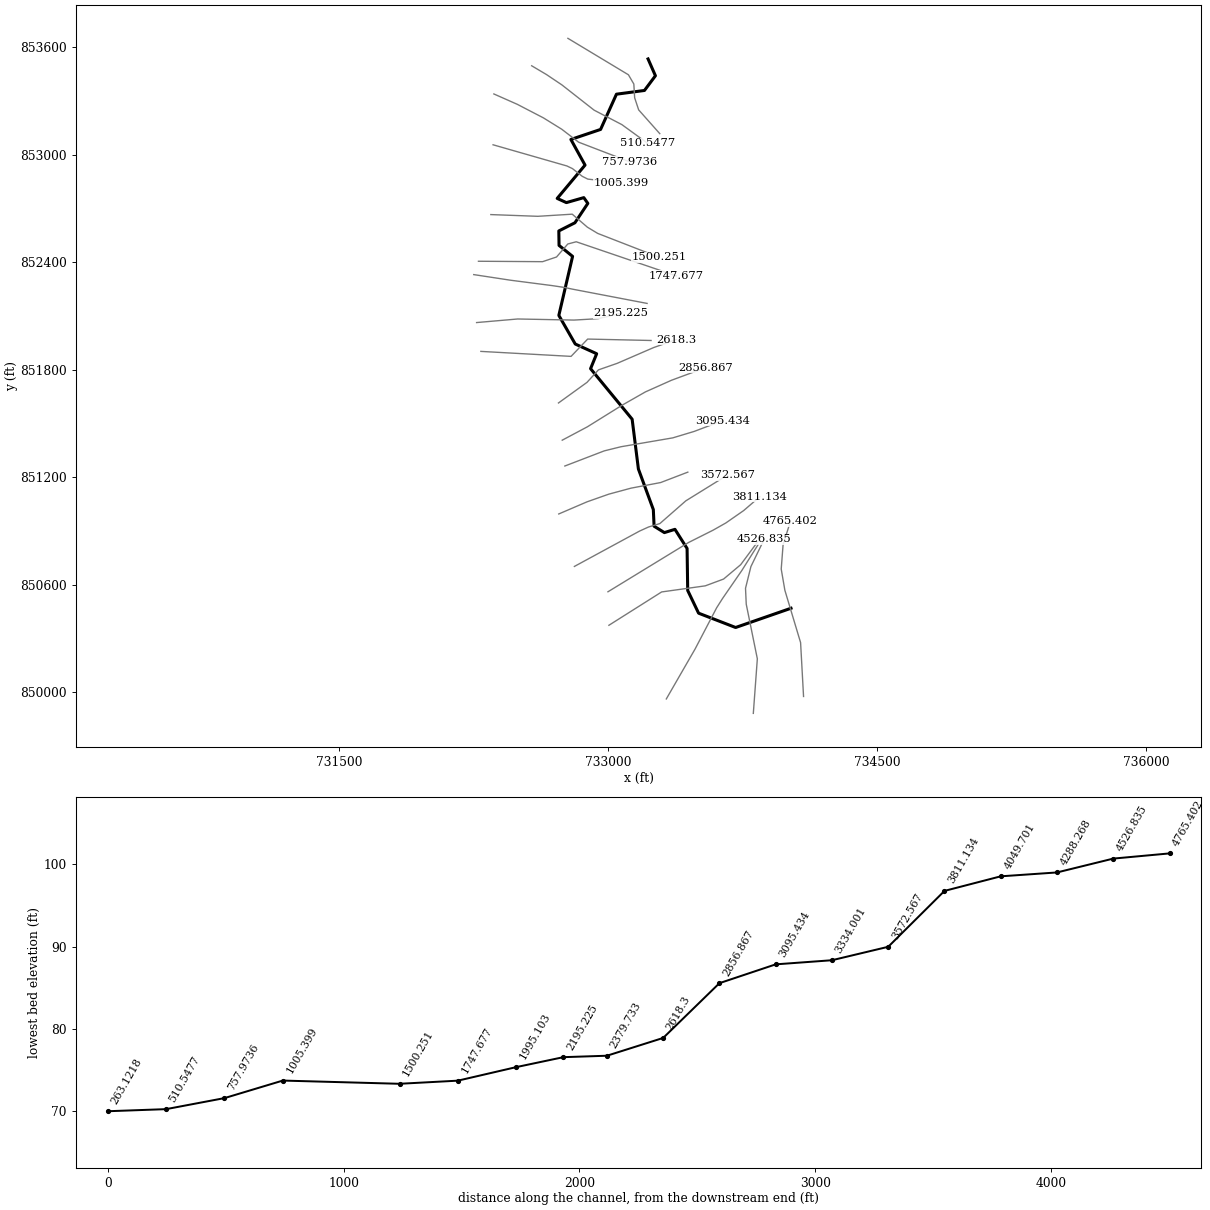
--- 14993_ras.prj (project) ---

Proj Title=14993
Current Plan=p01
Default Exp/Contr=0.3,0.1
English Units
Geom File=g01
Flow File=f01
Plan File=p01
Y Axis Title=Elevation
X Axis Title(PF)=Main Channel Distance
X Axis Title(XS)=Station
BEGIN DESCRIPTION:
RFD model 14993 exported to HEC-RAS
END DESCRIPTION:

--- 14993_ras.p01 (plan) ---

Plan Title=Plan 01
Program Version=4.10
Short Identifier=Plan 01
Geom File=g01
Flow File=f01
Subcritical Flow
Calc Critical at every XS
Secant Critical Depth

--- 14993_ras.f01 (steady flow) ---

Flow Title=Flow 01
Program Version=5.01
Number of Profiles= 6
Profile Names=10yr,25yr,50yr,100yr,100plus,500yr
River Rch & RM=14993,19,4765.402
  539.62   884.7  1214.7  1523.1 2223.73 3352.65
River Rch & RM=14993,19,4526.835
  544.71  893.14 1226.39 1537.84 2245.25 3380.89
River Rch & RM=14993,19,4288.268
  627.45  1030.2 1416.01 1776.88 2594.25 3832.89
River Rch & RM=14993,19,4049.701
  633.75 1040.65 1430.48 1795.14  2620.9 3867.12
River Rch & RM=14993,19,3811.134
  646.02 1061.02 1458.71 1830.75 2672.89 3933.75
River Rch & RM=14993,19,3572.567
  647.11 1062.83 1461.21 1833.91  2677.5 3939.65
River Rch & RM=14993,19,3334.001
  655.78 1077.23 1481.17 1859.11  2714.3 3986.73
River Rch & RM=14993,19,3095.434
  668.19 1097.85 1509.76  1895.2 2766.99 4054.04
River Rch & RM=14993,19,2856.867
  674.63 1108.55  1524.6 1913.95 2794.37 4088.98
River Rch & RM=14993,19,  2618.3
  681.87 1120.59 1541.29 1935.02 2825.13 4128.15
River Rch & RM=14993,19,2379.733
  685.88 1127.25 1550.53  1946.7 2842.18 4149.84
Boundary for River Rch & Prof#=14993,19,1
Up Type= 0
Dn Type= 2
Boundary for River Rch & Prof#=14993,19,2
Up Type= 0
Dn Type= 2
Boundary for River Rch & Prof#=14993,19,2
Up Type= 0
Dn Type= 2
Boundary for River Rch & Prof#=14993,19,2
Up Type= 0
Dn Type= 2
Boundary for River Rch & Prof#=14993,19,2
Up Type= 0
Dn Type= 2
Boundary for River Rch & Prof#=14993,19,2
Up Type= 0
Dn Type= 2

--- 14993_ras.g01 (geometry) ---

Geom Title=14993
Program Version=4.10

River Reach=14993,19
Reach XY= 30
734019.596296843850469.622777849733710.513497293850362.208746389
733503.916275024850442.069857523733443.152386159850568.805968553
 733439.68016395850803.180968553733371.971830606850909.951801866
733312.944052815850891.722635254733255.652386159 850927.31291303
733251.312108368851020.194857493733167.978775054851246.757357463
 733133.11766392851524.448329672732901.173219502851806.392774105
732935.200997263851889.726107448732815.756552786851943.892774165
732724.089886099852103.614996478732800.810713112852432.964146808
732725.289879739852494.162063524732723.987796396852574.891230151
732813.831546396852620.464146778732885.949280888852728.620450288
732863.379788339852760.738769278732766.157640427852732.960933819
732714.942341298852756.398302913732870.324238926 852942.16219759
732791.331055194853085.391413569732957.060713112853141.297480136
733045.602379769853337.912063435733201.852379769853358.745396793
733263.050296366853440.776647061733221.882739366853534.664140864

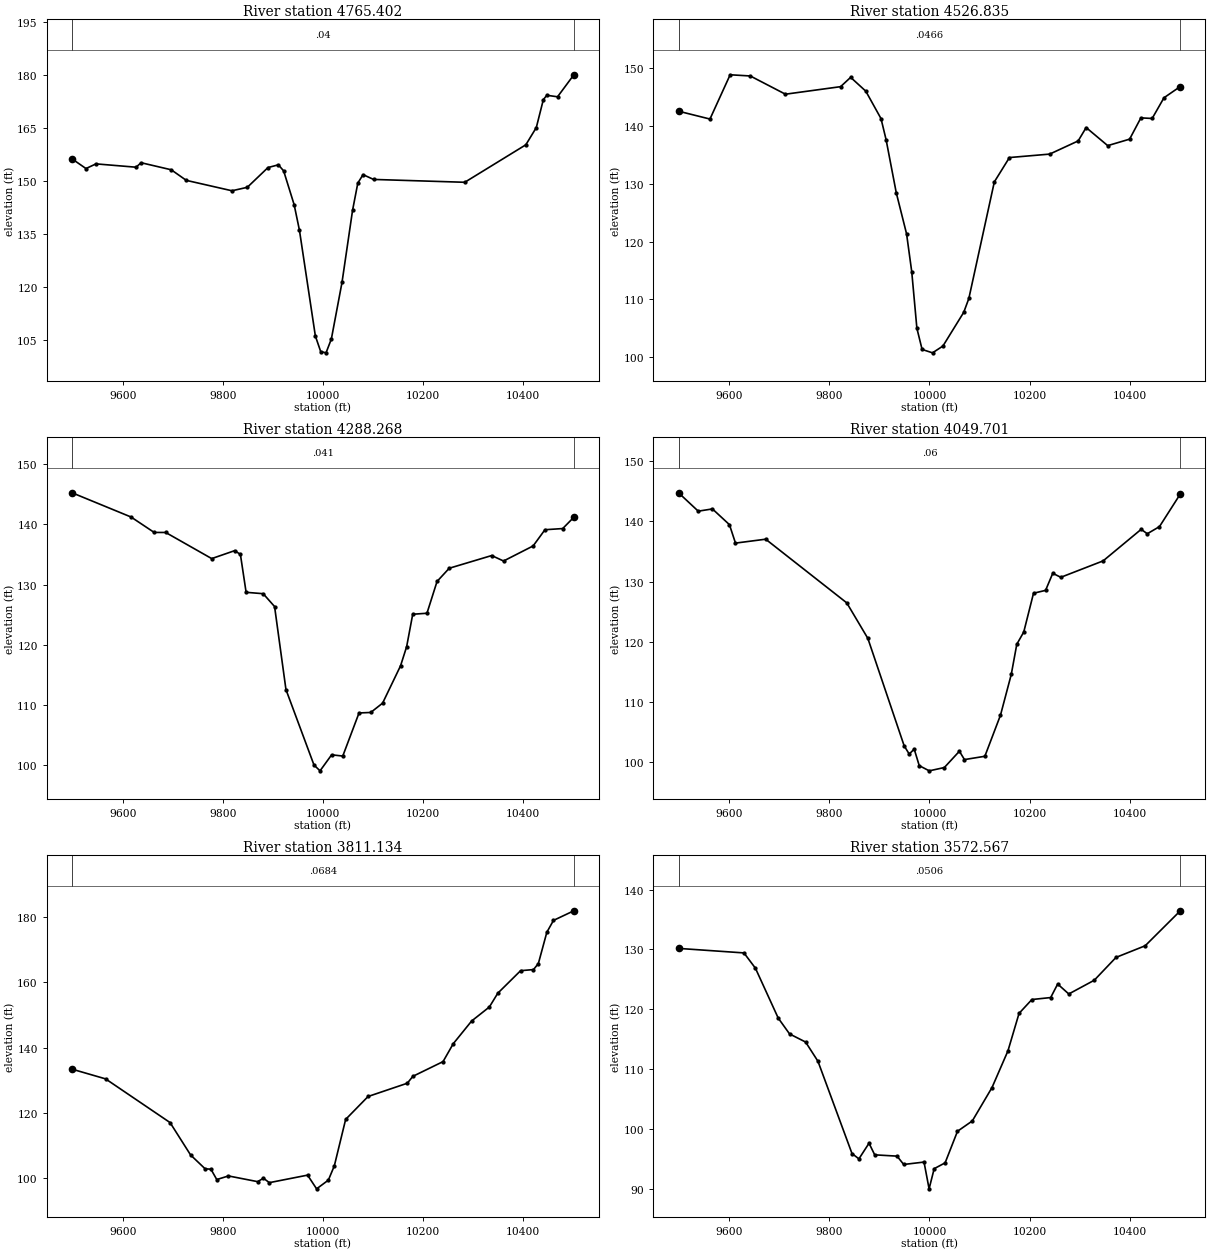
Type RM Length L Ch R = 1 ,4765.402,238.566900,238.566900,238.566900
XS GIS Cut Line= 6
 734089.54139639849977.265097471734073.017122218850277.962967671
733985.301531399850569.953669695733964.967329699  850688.2230773
733975.405597963850824.982849093734016.847684518850955.480467466
#Sta/Elev= 30
9499.058156.22299526.805 153.4929546.813 154.8149626.847153.86879636.851155.1376
9696.996153.1442 9727.13 150.1499818.264147.20339848.934148.18269890.219153.7728
 9910.94 154.5459921.437 152.8389942.464 143.2539952.978136.06629984.805106.1077
9995.453101.7068 10006.1101.348110016.73105.258910037.99121.273310059.09141.6926
10069.55149.379210080.01151.767510100.92150.412610283.06149.605210405.02160.2136
10425.91165.085810439.99 173.00210446.96174.222110468.32173.794310500.89180.0214
#Mann= 3 , 0 , 0
9499.058    0.04       09499.058    0.04       010500.89    0.04       0
#XS Ineff= 2 , 0
       0                               0
Bank Sta=9499.058,10500.89
Exp/Cntr=0.3,0.1

Type RM Length L Ch R = 1 ,4526.835,238.566900,238.566900,238.566900
XS GIS Cut Line= 6
733809.252266487849883.038951603733831.674094216850187.592957795
733769.778784276850492.158659521733765.740413678850581.075202004
733795.777762232850702.009596756733869.995855229850854.952896487
#Sta/Elev= 30
9499.074142.59669561.814141.23729602.117148.90989642.317148.70389712.488145.5433
9822.601146.84919842.682148.4641  9872.9146.07189903.293141.31549913.424137.6701
 9933.81128.43829954.353121.33139964.624 114.7939974.936104.96489985.328101.3049
10006.12100.715910026.91101.895310068.44107.737110078.65110.135610129.53130.3417
10159.69134.564310240.04135.161210296.89137.443610312.84139.7644 10355.9136.6286
10399.61137.752710422.11141.440210444.62141.337810468.22144.925810500.86146.8769
#Mann= 3 , 0 , 0
9499.074  0.0466       09499.074  0.0466       010500.86  0.0466       0
#XS Ineff= 2 , 0
       0                               0
Bank Sta=9499.074,10500.86
Exp/Cntr=0.3,0.1

Type RM Length L Ch R = 1 ,4288.268,238.566900,238.566900,238.566900
XS GIS Cut Line= 6
733323.800530171849963.576793677733484.630192046 850242.66082554
733604.515001448850471.976150808733637.109760769850523.448964632
733744.925674967850679.873085199733835.507196429850823.842250461
#Sta/Elev= 30
9499.018145.26789616.733141.24029662.988138.67279685.965 138.6679777.873134.3221
9823.798135.64749835.165135.01119846.533128.71649880.635128.4856 9903.37126.3511
9926.104112.53949982.053100.00179994.133 99.029810017.31101.694610039.55 101.488
   10072108.654710095.38108.735810119.05110.286810154.92116.496510167.06119.6752
10179.21125.068710207.65125.235910227.79 130.52510252.08132.716610336.93134.8316
10360.56133.921510419.63 136.42810443.26139.1244 10478.7 139.31810500.96141.2024
#Mann= 3 , 0 , 0
9499.018   0.041       09499.018   0.041       010500.96   0.041       0
#XS Ineff= 2 , 0
       0                               0
Bank Sta=9499.018,10500.96
Exp/Cntr=0.3,0.1

Type RM Length L Ch R = 1 ,4049.701,238.566900,238.566900,238.566900
XS GIS Cut Line= 6
733003.442641779850374.600485818733297.716030612850560.604421676
733541.311241313 850594.66256384 733643.31453679850632.501136761
733738.691148747850712.590144617733839.846861436850849.172110991
#Sta/Elev= 30
 9499.16144.76699538.508141.71049566.794142.08399600.785139.46769612.839 136.403
9673.112137.05289834.975126.47249877.091120.56589949.557102.71489959.611101.3492
9969.635102.16479979.65999.420079999.69898.5574410029.7799.1073710059.83101.8187
 10069.9100.427610110.63100.976810141.84107.808110163.33114.569510174.41119.5942
10188.28121.629410207.78 128.07110231.85128.550710246.18131.385810262.25130.7199
10346.74133.448610422.68138.692810434.86137.958210459.22139.144610500.84144.5683
#Mann= 3 , 0 , 0
 9499.16    0.06       0 9499.16    0.06       010500.84    0.06       0
#XS Ineff= 2 , 0
       0                               0
Bank Sta=9499.16,10500.84
Exp/Cntr=0.3,0.1

Type RM Length L Ch R = 1 ,3811.134,238.566900,238.566900,238.566900
XS GIS Cut Line= 6
732998.253709286850561.557682183733447.812929814 850836.43125182
733584.335797809850904.997910203733656.160031566850945.620205987
  733755.3161261851014.568247858733845.420267164851091.952255784
#Sta/Elev= 30
9499.024133.40019565.903130.4331 9694.67117.0605 9735.76107.12949764.616102.9222
9776.273 102.7879787.93199.622589811.246100.72799869.53498.980989881.192100.0341
9892.84998.670529969.238100.97639987.25996.7809510010.7299.4391410022.66103.8105
10045.26118.024810090.02125.038710168.35129.097510179.56131.215810239.74135.7141
10260.05141.175210296.88148.148210332.19152.423110349.08156.648710394.58163.5364
 10420.3163.877610430.03165.709710446.99175.301810460.23178.925110500.93181.8707
#Mann= 3 , 0 , 0
9499.024  0.0684       09499.024  0.0684       010500.93  0.0684       0
#XS Ineff= 2 , 0
       0                               0
Bank Sta=9499.024,10500.93
Exp/Cntr=0.3,0.1

Type RM Length L Ch R = 1 ,3572.567,238.566900,238.566900,238.566900
XS GIS Cut Line= 6
732810.896249215850702.922731404733174.590401457850900.240216097
733224.590960806850922.933301691733287.900363278850942.163113965
733432.666105138851068.932056659733665.249356426851212.977024086
#Sta/Elev= 30
9499.072130.18329629.664129.42889652.554126.87249698.073118.53149720.732115.8798
9752.766114.52249777.377111.31089845.35295.876699859.15694.988649879.33997.60667
9890.66895.661149935.27595.446369948.57694.05015 9989.1594.45309 9999.2589.97583
10009.4193.3496310031.2494.3209510055.9399.60245 10085.5101.328410124.83106.9117
10156.64113.043910178.81119.316210204.46121.634110241.97121.963610255.92124.2245
10278.12122.5628   10329 124.86110372.41128.679510430.62130.624210500.77136.4751
#Mann= 3 , 0 , 0
9499.072  0.0506       09499.072  0.0506       010500.77  0.0506       0
#XS Ineff= 2 , 0
       0                               0
Bank Sta=9499.072,10500.77
Exp/Cntr=0.3,0.1

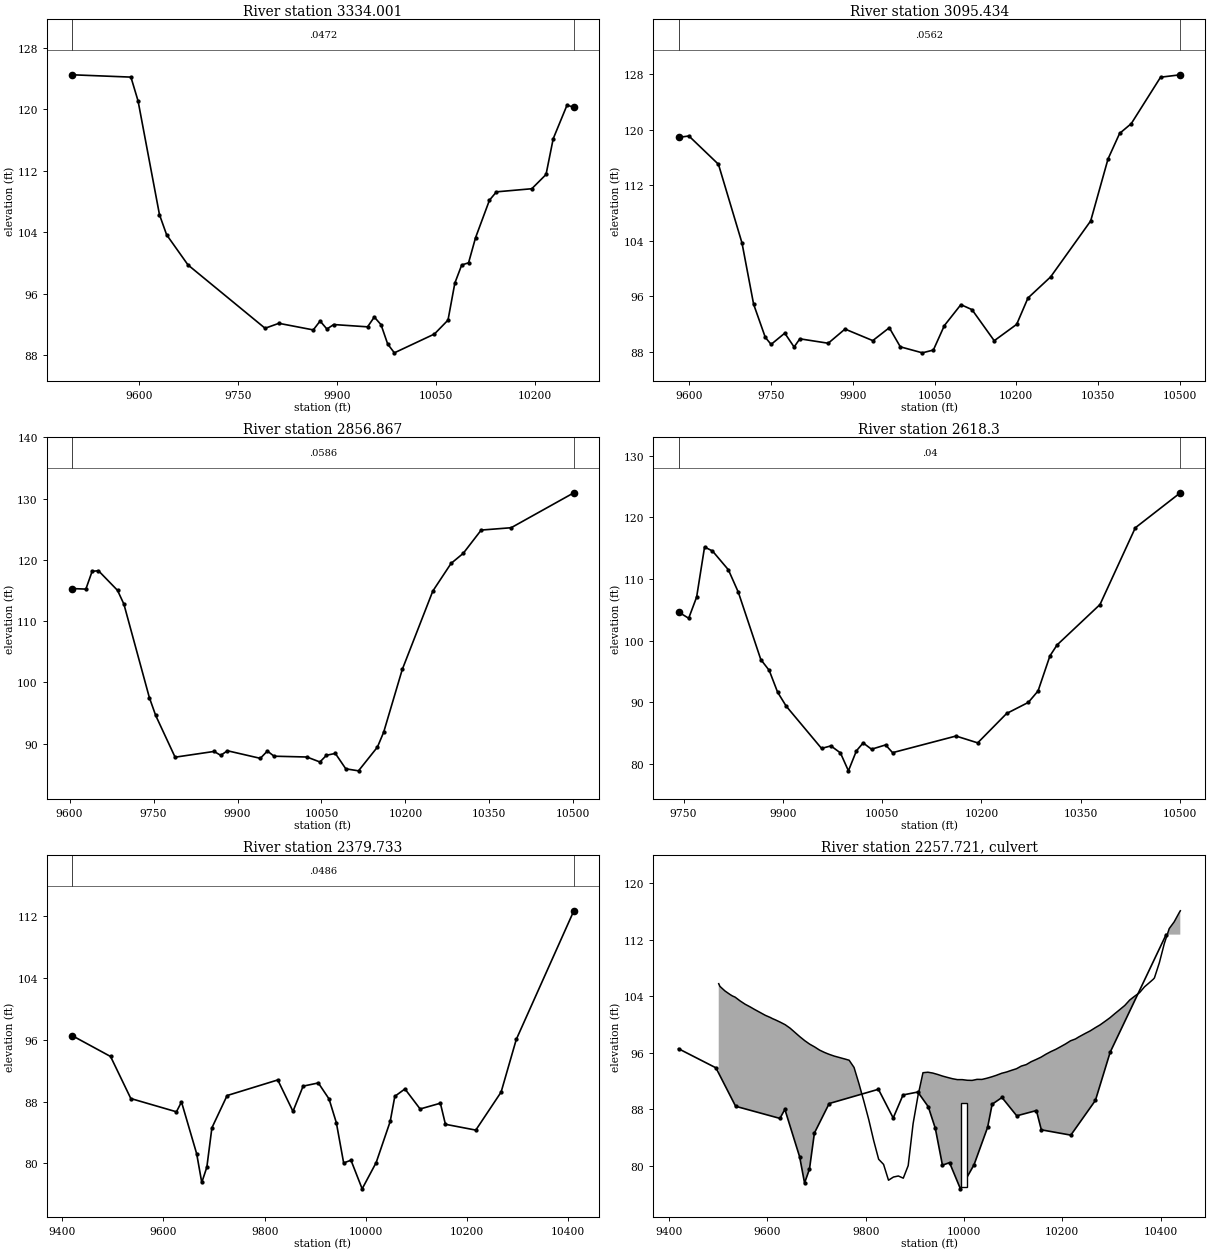
Type RM Length L Ch R = 1 ,3334.001,238.566900,238.566900,238.566900
XS GIS Cut Line= 6
732723.596339033850995.647276323732881.681772398851063.492256148
733003.065253868851106.271802045733127.475319931851139.852875566
733292.202521735851170.984630705733443.773252746851229.032324193
#Sta/Elev= 30
 9499.03124.49229588.157 124.1899598.971121.09179631.413 106.2979642.227103.6875
9674.61899.765559791.30491.53541 9812.2392.176299864.306 91.31979874.65592.47336
9884.95391.43429 9895.2592.018219946.534 91.71889956.71592.993539966.89792.00081
9976.99989.484029987.087  88.33910047.8190.7870810068.34 92.595310078.7197.41348
10089.0899.7558210099.49100.048310110.04103.306710131.12108.188510141.67109.2708
10195.22109.675610216.79111.526610227.66 116.17910248.63120.555110258.93120.2484
#Mann= 3 , 0 , 0
 9499.03  0.0472       0 9499.03  0.0472       010258.93  0.0472       0
#XS Ineff= 2 , 0
       0                               0
Bank Sta=9499.03,10258.93
Exp/Cntr=0.3,0.1

Type RM Length L Ch R = 1 ,3095.434,238.566900,238.566900,238.566900
XS GIS Cut Line= 6
732757.592835921851263.229366159732977.386269705851347.650107873
733070.703253149851370.777500021733359.984707778851420.323839886
733479.701198177851456.386983026733638.715598253851516.708505634
#Sta/Elev= 30
9580.387118.88469599.427119.0887 9653.61115.00989696.813103.6672 9718.1694.83631
9739.506 90.0785 9750.1889.052499775.27890.671469792.41688.678829802.93889.85668
9855.01589.219499885.81191.263589936.71489.599949967.05391.455189987.27988.70369
10027.6987.8367510047.8888.2393310068.08 91.766710098.3994.7839710118.7794.06223
10159.5689.58205 10200.791.9413210221.4395.73802   1026398.77866 10336.5106.8475
10368.35115.782910389.58119.457710410.95120.868910464.72127.560410500.97127.9102
#Mann= 3 , 0 , 0
9580.387  0.0562       09580.387  0.0562       010500.97  0.0562       0
#XS Ineff= 2 , 0
       0                10098.96       0
Bank Sta=9580.387,10500.97
Exp/Cntr=0.3,0.1

Type RM Length L Ch R = 1 ,2856.867,238.566900,238.566900,238.566900
XS GIS Cut Line= 6
732743.024334926851407.380849741732883.408577441851482.004921546
733077.201348584 851602.61564418733206.706479186851676.506246876
733352.668628524851741.756399769 733540.44748394851811.166379417
#Sta/Elev= 30
9604.411115.3232 9629.05115.22989640.262118.13449651.531 118.2369685.637115.0253
9697.005112.7798 9742.4897.521499753.848 94.58639788.49187.775769858.19488.71674
9870.05788.07208 9881.9688.827479940.80187.58645 9953.3888.783729965.28487.93673
10024.0487.8047510047.2986.9919510058.9188.0867510074.7988.3919910093.4785.87641
10116.1985.5460910150.0489.4298910161.1391.8497410194.39102.105110248.96114.9107
10281.56119.424910303.26121.065410335.39124.872610388.95125.256910500.98130.9655
#Mann= 3 , 0 , 0
9604.411  0.0586       09604.411  0.0586       010500.98  0.0586       0
#XS Ineff= 2 , 0
       0                               0
Bank Sta=9604.411,10500.98
Exp/Cntr=0.3,0.1

Type RM Length L Ch R = 1 ,  2618.3,238.566900,238.566900,238.566900
XS GIS Cut Line= 6
732722.043393016 851614.98174871732881.159175981851729.928404132
732945.211400617851799.721307306733050.252890629 851836.35008653
733253.404927825851924.307615675733379.516889173851968.816574765
#Sta/Elev= 30
9742.409104.64599757.763 103.6419769.752107.07889781.742 115.2029793.731114.5575
 9817.71111.51069832.794107.8564 9866.7396.93979 9879.4595.179699892.10491.64792
9905.043 89.38449958.515 82.51679972.69582.924429987.05281.787149999.15878.87606
10011.22 82.1222 10021.483.4077110034.0782.38377 10055.383.0817410065.8981.82581
10161.7184.5251210194.5183.4163910238.2488.1837310271.0489.9846310285.7291.83772
10303.6897.5357610314.5299.3142710379.34105.8695 10432.7118.324410500.73124.0066
#Mann= 3 , 0 , 0
9742.409    0.04       09742.409    0.04       010500.73    0.04       0
#XS Ineff= 2 , 0
       0                               0
Bank Sta=9742.409,10500.73
Exp/Cntr=0.3,0.1

Type RM Length L Ch R = 1 ,2379.733,184.507700,184.507700,184.507700
XS GIS Cut Line= 4
732289.046634606851902.782954661732792.342594594851875.000000015
 732885.00000003851971.587276474 733238.77184242851963.655409276
#Sta/Elev= 30
9419.42196.55735 9495.4993.850889535.55188.403339625.68886.686569635.70387.96198
9665.749 81.24129675.76477.532699685.77979.510639695.79484.61104 9725.8488.79264
9825.99290.812839856.038 86.74539876.06890.009899906.11490.424399927.32288.34999
9941.76785.268899956.21280.059119970.65780.41784 9992.7776.7088910020.4980.11633
 10048.285.4444710057.3388.6921610077.3389.6485410107.3487.0526810147.3587.79901
10157.3585.0690110217.3784.3169210267.3889.2377210297.3996.0612510411.19112.7232
#Mann= 3 , 0 , 0
9419.421  0.0486       09419.421  0.0486       010411.19  0.0486       0
#XS Ineff= 2 , 0
       09939.768        10061.45       0
Bank Sta=9419.421,10411.19
Exp/Cntr=0.3,0.1

Type RM Length L Ch R = 2 ,2257.721,,,
Bridge Culvert--1,0,-1,-1, 0
Deck Dist Width WeirC Skew NumUp NumDn MinLoCord MaxHiCord MaxSubmerge Is_Ogee
38.254,108,2.6,0,109,109, , , 0.95, 0, 0,0,,
 9501.14 9503.64 9513.90 9524.16 9529.10 9534.42 9544.68 9554.94 9565.20 9573.87
 9575.46 9585.72 9595.97 9606.23 9610.57 9616.34 9626.35 9636.35 9646.35 9656.35
 9666.35 9676.35 9686.35 9696.35 9706.36 9716.36 9722.29 9726.36 9736.36 9746.36
 9748.37 9756.18 9756.37 9766.39 9776.40 9786.42 9796.43 9806.45 9816.46 9826.47
 9836.49 9846.50 9856.52 9866.53 9876.55 9886.56 9896.58 9906.59 9916.61 9926.62
 9934.19 9936.63 9946.63 9956.63 9966.63 9976.63 9986.63 9996.6310006.6310016.63
10026.6310035.9710036.6310046.6310056.6310066.6310068.6410072.2110076.6410086.64
10096.6510106.6610116.6710126.6710136.6810146.6910156.6910166.7010176.7110186.72
10196.7210206.7310216.7410226.7410233.3410236.7610246.8110256.8510266.8910275.95
10276.9310286.9810297.0210307.0610317.1010327.1410337.1910347.2310357.2710367.31
10377.3510385.1610387.4010397.4410407.4810417.5210427.5710437.6110440.09
  105.77  105.39  104.74  104.24  104.03  103.87  103.33  102.86  102.48  102.13
  102.07  101.68  101.29  100.98  100.82  100.65  100.32   99.96   99.47   98.86
   98.25   97.69   97.20   96.81   96.36   96.03   95.86   95.75   95.51   95.32
   95.28   95.13   95.13   94.93   93.91   91.60   89.11   86.48   83.52   80.90
   80.17   77.93   78.38   78.53   78.22   80.00   85.96   89.94   93.16   93.23
   93.14   93.11   92.91   92.68   92.49   92.31   92.18   92.18   92.09   92.07
   92.22   92.21   92.21   92.38   92.58   92.81   92.87   92.96   93.08   93.26
   93.50   93.72   94.10   94.31   94.72   95.03   95.36   95.78   96.15   96.47
   96.85   97.24   97.68   97.94   98.22   98.35   98.73   99.09   99.53   99.90
   99.94  100.44  100.95  101.54  102.11  102.69  103.46  104.00  104.51  105.33
  105.93  106.41  106.59  108.74  111.45  113.58  114.53  115.81  116.10
                                                                                
                                                                                
                                                                                
                                                                                
                                                                                
                                                                                
                                                                                
                                                                                
                                                                                
                                                                                
                                                                        
 9501.14 9503.64 9513.90 9524.16 9529.10 9534.42 9544.68 9554.94 9565.20 9573.87
 9575.46 9585.72 9595.97 9606.23 9610.57 9616.34 9626.35 9636.35 9646.35 9656.35
 9666.35 9676.35 9686.35 9696.35 9706.36 9716.36 9722.29 9726.36 9736.36 9746.36
 9748.37 9756.18 9756.37 9766.39 9776.40 9786.42 9796.43 9806.45 9816.46 9826.47
 9836.49 9846.50 9856.52 9866.53 9876.55 9886.56 9896.58 9906.59 9916.61 9926.62
 9934.19 9936.63 9946.63 9956.63 9966.63 9976.63 9986.63 9996.6310006.6310016.63
10026.6310035.9710036.6310046.6310056.6310066.6310068.6410072.2110076.6410086.64
10096.6510106.6610116.6710126.6710136.6810146.6910156.6910166.7010176.7110186.72
10196.7210206.7310216.7410226.7410233.3410236.7610246.8110256.8510266.8910275.95
10276.9310286.9810297.0210307.0610317.1010327.1410337.1910347.2310357.2710367.31
10377.3510385.1610387.4010397.4410407.4810417.5210427.5710437.6110440.09
  105.77  105.39  104.74  104.24  104.03  103.87  103.33  102.86  102.48  102.13
  102.07  101.68  101.29  100.98  100.82  100.65  100.32   99.96   99.47   98.86
   98.25   97.69   97.20   96.81   96.36   96.03   95.86   95.75   95.51   95.32
   95.28   95.13   95.13   94.93   93.91   91.60   89.11   86.48   83.52   80.90
   80.17   77.93   78.38   78.53   78.22   80.00   85.96   89.94   93.16   93.23
   93.14   93.11   92.91   92.68   92.49   92.31   92.18   92.18   92.09   92.07
   92.22   92.21   92.21   92.38   92.58   92.81   92.87   92.96   93.08   93.26
   93.50   93.72   94.10   94.31   94.72   95.03   95.36   95.78   96.15   96.47
   96.85   97.24   97.68   97.94   98.22   98.35   98.73   99.09   99.53   99.90
   99.94  100.44  100.95  101.54  102.11  102.69  103.46  104.00  104.51  105.33
  105.93  106.41  106.59  108.74  111.45  113.58  114.53  115.81  116.10
                                                                                
                                                                                
                                                                                
                                                                                
                                                                                
                                                                                
                                                                                
                                                                                
                                                                                
                                                                                
                                                                        
BR Coef=-1 , 0 , 0 ,, 0 ,,,0.8,-1,,0,
WSPro=,,,, 1 ,,,, 0 ,,,, 0 ,,,,-1 ,-1 ,-1 , 0 , 0 , 0 , 0 , 0
Culvert=2,12,12,108,0.013,0.04,1,58,1,76.903,10000,76.537,10000,Culvert #1, 0, 38.254
Culvert Bottom n=0.013
BC Design=,, 0 ,, 0 ,,,,,,

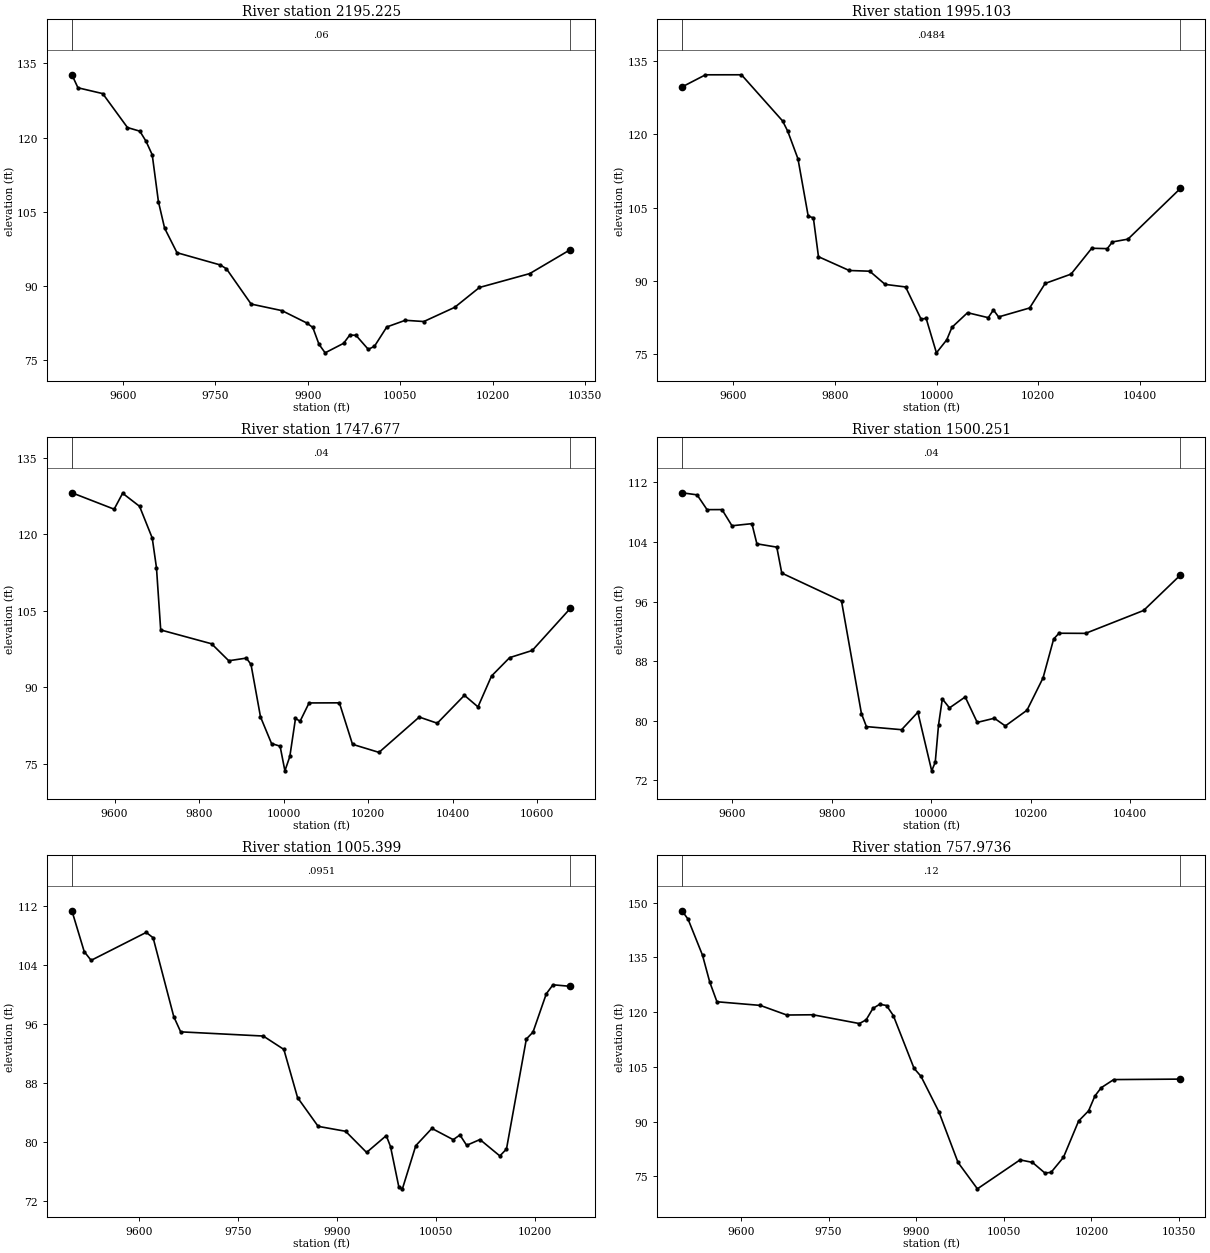
Type RM Length L Ch R = 1 ,2195.225,200.122200,200.122200,200.122200
XS GIS Cut Line= 5
732265.216553581852063.661033645732494.383220208852083.626311421
732808.619331343852077.549922555732943.167942447852085.362422555
733069.286496475852114.524971074
#Sta/Elev= 30
9517.304132.69829527.125130.07129567.276128.89489607.428122.03999627.504121.3047
9637.542119.2656 9647.58 116.5349657.617 107.0759667.655101.71799687.73196.75879
9757.95894.28572 9767.9693.508939807.96786.387129857.97785.058969897.98482.57912
9907.98681.663149917.98878.27876 9927.9976.534529957.99578.461399967.99780.13498
9977.99980.076949998.00377.23806   1000877.8593110028.0181.7613210058.0183.10903
10088.0682.8590910138.1485.7254910178.2189.7347510259.8792.5407210325.8697.38933
#Mann= 3 , 0 , 0
9517.304    0.06       09517.304    0.06       010325.86    0.06       0
#XS Ineff= 2 , 0
       09958.409        10066.81       0
Bank Sta=9517.304,10325.86
Exp/Cntr=0.3,0.1

Type RM Length L Ch R = 1 ,1995.103,247.425900,247.425900,247.425900
XS GIS Cut Line= 6
 732249.26485657 852331.26803383732454.266324492852299.973101665
732685.619727191852270.063016204732759.038045714852259.009619472
732798.832521741852250.340415342733216.521009356 852170.50265117
#Sta/Elev= 30
9499.011129.66299545.276132.14949616.087132.15599697.014122.72059707.127120.6251
9727.294114.9724 9747.46103.24199757.543102.92789767.62794.971579828.12692.15257
9868.45992.006779898.70889.313859939.04188.786479969.37682.228979979.488 82.3566
9999.71175.3214210020.0177.9829610030.2580.5416610060.9283.5250110101.6482.50999
10111.8284.0927210122.0182.6604210183.0984.4934310213.6389.5064410264.5491.41238
10305.2696.6941910335.8196.6211210345.9997.9902610376.5398.5612810479.89108.9422
#Mann= 3 , 0 , 0
9499.011  0.0484       09499.011  0.0484       010479.89  0.0484       0
#XS Ineff= 2 , 0
       0                               0
Bank Sta=9499.011,10479.89
Exp/Cntr=0.3,0.1

Type RM Length L Ch R = 1 ,1747.677,247.425900,247.425900,247.425900
XS GIS Cut Line= 6
732275.508519411852405.730657026732633.364429295852403.391330555
732711.318373561852429.557519749732773.966435492852501.999078989
732821.208888501852514.463723496733379.391521722852324.260636464
#Sta/Elev= 30
9499.233128.0982 9599.15 124.8889619.207128.00339659.233125.45019689.253119.2387
9699.259113.42529709.266101.24959829.65398.540089870.26895.220039911.87995.73943
9922.862 94.49539945.305 84.23879971.41479.016359991.68278.5006310003.0373.67319
10014.6776.48617 10028.183.9275410038.9583.38504 10060.286.9635910131.8886.98299
10162.95 78.866410225.5777.28555 10320.884.2008110363.4182.9931910427.6188.45824
10459.7186.1922710491.8192.2398410534.6295.8319810588.1297.2349710678.42105.4959
#Mann= 3 , 0 , 0
9499.233    0.04       09499.233    0.04       010678.42    0.04       0
#XS Ineff= 2 , 0
       0                               0
Bank Sta=9499.233,10678.42
Exp/Cntr=0.3,0.1

Type RM Length L Ch R = 1 ,1500.251,494.851700,494.851700,494.851700
XS GIS Cut Line= 6
732344.668309616852666.158749881732607.044254186852656.513391389
732798.883305729852668.409824931732883.361012457852595.887087604
732941.026286258852561.106765326733283.174796107 852428.06808897
#Sta/Elev= 30
9499.177110.5904 9529.56110.31229549.594108.32929579.646108.3347 9599.68106.1656
9639.737106.44879649.738103.74529689.742 103.2989699.74399.81778 9819.7796.07051
9859.79880.978839869.83979.226519940.527 78.8107 9973.1881.15198   1000173.29219
10008.1674.4518610014.7279.4328210022.3782.9415110036.7481.7331110068.3383.20262
10092.4879.7887210126.93 80.348410148.97 79.313610192.4581.4181810224.7485.75294
10246.0990.9739910256.7691.7504310310.1291.7319410426.8794.8053110500.9399.56525
#Mann= 3 , 0 , 0
9499.177    0.04       09499.177    0.04       010500.93    0.04       0
#XS Ineff= 2 , 0
       0                               0
Bank Sta=9499.177,10500.93
Exp/Cntr=0.3,0.1

Type RM Length L Ch R = 1 ,1005.399,247.425900,247.425900,247.425900
XS GIS Cut Line= 6
732357.106315847853055.637178641732769.327866695852937.379564297
732800.189442662852922.652470521732854.564275453852879.760654146
732885.537416949852864.153463028733071.117539415852843.298569597
#Sta/Elev= 30
9499.066111.35959517.712105.82129528.132104.64269611.493108.42869621.913 107.702
9653.173 97.00939663.59394.955259788.53594.387459819.66692.57451 9840.42 86.0448
9871.551 82.15089913.05881.482869944.83878.615119974.58480.893339981.00579.41272
9993.71373.89431    999973.6840810019.2479.53232 10043.681.8717110075.8580.34705
10086.0280.9818810096.1879.5801410116.32 80.3647 10146.478.1412510156.4279.07356
 10186.593.9873610196.5394.9163110216.65100.109710226.76101.331910253.18101.1207
#Mann= 3 , 0 , 0
9499.066  0.0951       09499.066  0.0951       010253.18  0.0951       0
#XS Ineff= 2 , 0
       0                               0
Bank Sta=9499.066,10253.18
Exp/Cntr=0.3,0.1

Type RM Length L Ch R = 1 ,757.9736,247.425900,247.425900,247.425900
XS GIS Cut Line= 6
732361.563995965853339.234463372732492.402157718 853281.34034048
732638.184051017853205.676291964732740.150918991853142.478488189
732834.478186912 853070.13963877 733120.99113655 852960.14528283
#Sta/Elev= 30
9499.075147.7883 9509.54145.48529534.253135.60899546.574128.28169558.966122.8441
9633.106121.84619678.544119.20539723.203119.27589802.802116.86739814.356117.8868
9825.991121.01449837.627122.15659849.263121.81439860.899119.06549896.359104.5961
9908.309102.39269938.73592.731259971.68378.7841310004.8371.5479210077.8379.48752
   1009978.8055310120.1775.9200310130.7676.0306710152.1780.1919510178.12 90.1475
10195.1992.9382510205.9596.99415 10216.7 99.264810238.21101.5051 10352.5101.6355
#Mann= 3 , 0 , 0
9499.075    0.12       09499.075    0.12       0 10352.5    0.12       0
#XS Ineff= 2 , 0
       0                               0
Bank Sta=9499.075,10352.5
Exp/Cntr=0.3,0.1

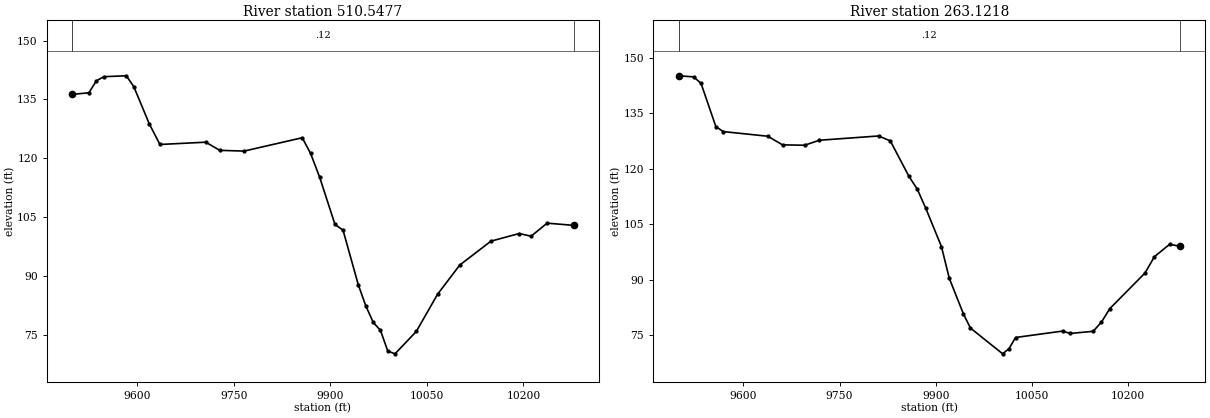
Type RM Length L Ch R = 1 ,510.5477,247.425900,247.425900,247.425900
XS GIS Cut Line= 6
732572.497349422853496.477246713732655.303960128853447.386666747
732740.668329112853390.149253385732920.960007531853248.755450717
733075.692663105853168.225089563733218.537608771853064.639610293
#Sta/Elev= 30
9499.067136.27399525.227136.69729536.852139.73839548.477140.79229583.353141.0209
9594.978138.23789619.045 128.7499635.529123.52589706.712124.10819728.481122.0325
9766.215121.84249856.502125.2377  9869.4121.28419883.528115.20479907.391 103.147
9919.855101.72319943.61187.78381 9955.2482.414329966.82578.216749978.07376.17135
9989.32170.9359510000.5970.2047210033.7275.9197710066.6985.3721210101.0992.80317
10149.5398.89812 10193.5100.847710211.93100.163110236.89103.489810278.37102.9184
#Mann= 3 , 0 , 0
9499.067    0.12       09499.067    0.12       010278.37    0.12       0
#XS Ineff= 2 , 0
       0                               0
Bank Sta=9499.067,10278.37
Exp/Cntr=0.3,0.1

Type RM Length L Ch R = 1 ,263.1218,0.000000,0.000000,0.000000
XS GIS Cut Line= 6
732774.708224775853649.568628823733112.460996162853446.183641715
733142.591458908853394.520423202733147.097868041853317.878313664
733169.535499212853250.356009192 733287.28389522853117.761740735
#Sta/Elev= 30
 9499.19 145.117 9522.66144.82049534.226143.08129557.359131.36289568.925130.0285
9638.264128.77479661.213126.44779695.637126.33769718.586127.69079810.765 128.844
9829.146127.52329858.169117.93029871.118114.49069884.234109.3798 9908.8198.95873
 9921.0790.362589943.19380.695859953.94976.9328810004.2569.9493510014.2671.38864
10024.2674.3648510097.8276.10719 10109.375.4541410145.1976.0378510158.1578.51735
10171.1582.1693810225.8991.7775510240.7196.21543 10264.499.5616210281.0599.01019
#Mann= 3 , 0 , 0
 9499.19    0.12       0 9499.19    0.12       010281.05    0.12       0
#XS Ineff= 2 , 0
       0                               0
Bank Sta=9499.19,10281.05
Exp/Cntr=0.3,0.1